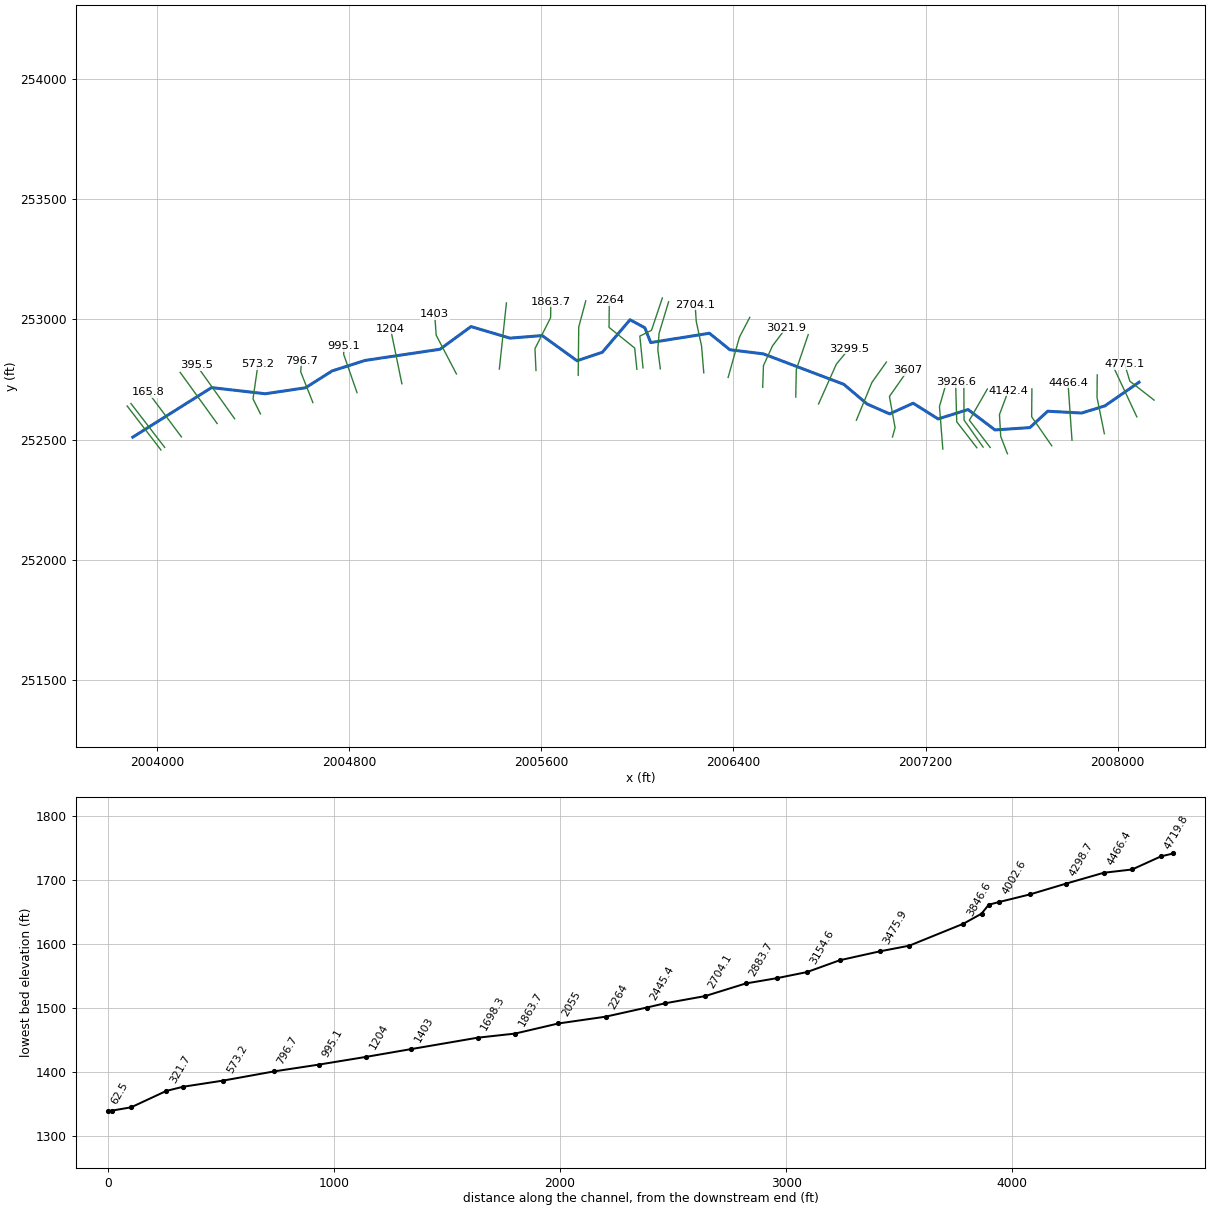
--- TUGCK.prj (project) ---

Proj Title=TUGCK
Current Plan=p01
Default Exp/Contr=0,0
English Units
Geom File=g01
Flow File=f01
Plan File=p01
BEGIN DESCRIPTION:
END DESCRIPTION:
DSS Export Rating Curves= 0
DSS Export Rating Curve Sorted= 0
DSS Export Volume Flow Curves= 0
DXF OffsetX= 0
DXF OffsetY= 0
DXF ScaleX= 0
DXF ScaleY= 0

--- TUGCK.p01 (plan) ---

Plan Title=Floodplain
Program Version=4.00
Geom File=g01
Flow File=f01
K Sum by GR=0
Std Step Tol=0.01
Critical Tol=0.01
Num of Std Step Trials=20
Max Error Tol=0.3
Flow Tol Ratio=0.001
Split Flow NTrial=30
Split Flow Tol=0.02
Split Flow Ratio=0.02
Log Output Level=0
Friction Slope Method=1
Unsteady Friction Slope Method=2
Unsteady Bridges Friction Slope Method=1
Global Log Level=0
CheckData=False
Run HTab=0
Run UNet=0
Run PostProcess=0
UNET Theta=0
UNET Theta Warmup=0
UNET ZTol=0
UNET ZSATol=0
UNET MxIter=0
UNET MaxInSteps=0
UNET DtIC=0
UNET DtMin=0
UNET MaxCRTS=0
UNET WFStab=0
UNET SFStab=0
UNET WFX=0
UNET SFX=0
UNET DSS MLevel=0
UNET DZMax Abort=0
UNET Convert EG Bridges=0
UNET Use Existing IB Tables=0
UNET Froude Limit=0
UNET Froude Power=0
Write IC File=0
Echo Input=False
Echo Output=False
Write Detailed=0

--- TUGCK.f01 (steady flow) ---

Flow Title=2010 USGS WV Regression Equation
Program Version=5.03
Number of Profiles= 1
Profile Names=P100yr
River Rch & RM=TUGCK,Main            ,4775.1
473.5552
River Rch & RM=TUGCK,Main            ,4466.4
579.5767
River Rch & RM=TUGCK,Main            ,3846.6
581.3788
River Rch & RM=TUGCK,Main            ,3475.9
657.8344
River Rch & RM=TUGCK,Main            ,2883.7
690.6764
River Rch & RM=TUGCK,Main            ,165.8
737.2895
Boundary for River Rch & Prof#=TUGCK,Main            , 1
Up Type= 0
Dn Type= 3
Dn Slope=0.05966
DSS Import GetInterval= 0
DSS Import GetPeak= 0
DSS Import FillOption= 0

--- TUGCK.g01 (geometry) ---

Geom Title=LiDAR
Program Version=4.10

River Reach=TUGCK           ,Main
Reach XY= 30
     2008089.495      252738.701     2007947.134       252640.09
     2007850.296      252610.231      2007708.94      252617.867
     2007634.845      252549.641     2007489.359      252539.918
     2007377.286      252624.768     2007252.553      252585.752
     2007148.523      252651.201      2007050.47      252606.759
      2006956.72      252647.905     2006859.526      252729.991
     2006524.428      252856.759     2006385.152      252873.889
     2006299.735      252942.639     2006055.291       252903.75
     2006030.852      252965.439      2005969.18      252998.889
     2005853.902      252863.473     2005748.346      252828.056
     2005603.248      252932.974     2005469.072      252922.263
      2005306.68      252970.417     2005177.513      252875.973
     2004865.707      252829.445     2004728.207      252785.695
      2004617.31      252715.439     2004449.735      252690.556
     2004226.124      252716.251     2003897.788      252509.789

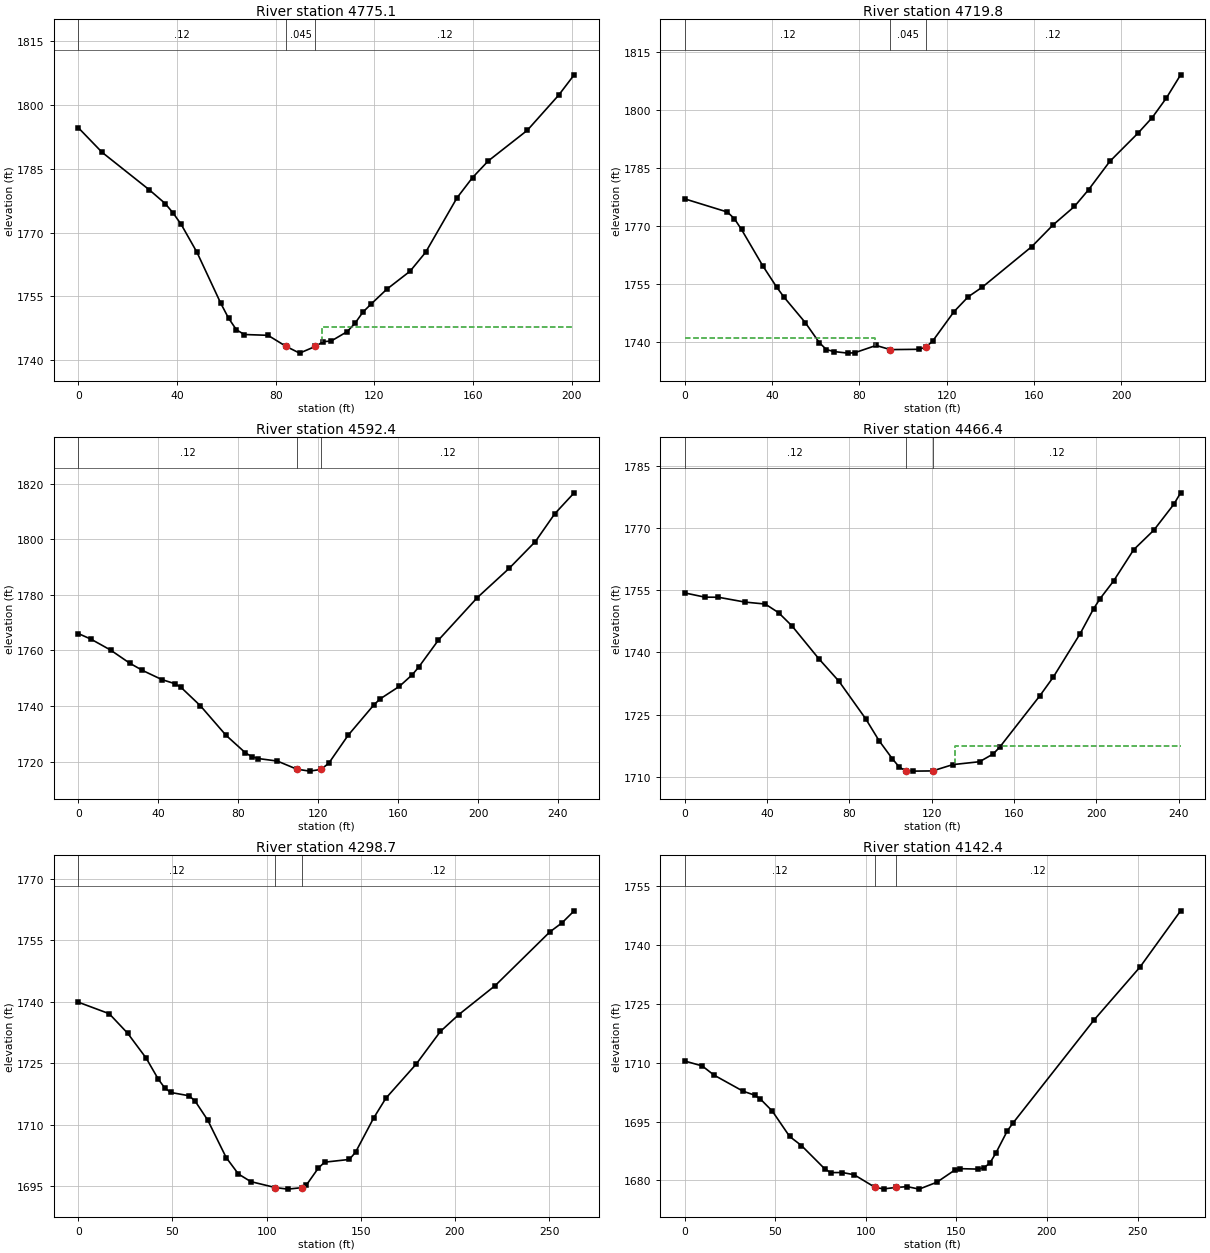
Type RM Length L Ch R = 1 ,4775.1  ,66.1,55.3,44.8
XS GIS Cut Line= 3
     2008152.078      252664.184     2008051.055      252743.078
     2008029.974      252812.807
#Sta/Elev= 30
       0  1794.6     9.6 1788.84    28.8 1780.01    35.2 1776.81    38.4  1774.6
    41.7  1771.9    48.1 1765.35    57.7 1753.44    60.9 1749.89    64.1 1747.16
    67.3 1746.06    76.9 1745.87   84.281743.249    89.7 1741.69    96.1 1743.27
    99.3 1744.38   102.5 1744.53     109 1746.74   112.2 1748.73   115.4 1751.34
   118.6 1753.16     125 1756.67   134.5 1760.93   140.8 1765.37   153.5 1778.14
   159.8  1782.9   166.2 1786.82     182 1793.99   194.7 1802.23     201 1807.02
#Mann= 3 ,-1 , 0
       0     .12       0   84.28    .045       0    96.1     .12       0
#XS Ineff= 2 , 0
                           98.81         1747.92
Permanent Ineff=
       F       F
Bank Sta=84.28,96.1
XS Rating Curve= 0 ,0
Exp/Cntr=0.3,0.1

Type RM Length L Ch R = 1 ,4719.8  ,132.1,127.4,121.3
XS GIS Cut Line= 2
     2008080.288      252594.282     2007983.894       252800.11
#Sta/Elev= 30
       0 1776.96    19.5 1773.56    22.7 1771.86      26 1769.04    35.7 1759.68
    42.2 1754.06    45.5 1751.52    55.2 1744.97    61.7 1739.75    64.9 1737.98
    68.2 1737.47    74.7 1737.05    77.9 1737.15    87.7 1739.04    94.2 1737.96
   107.2 1738.04   110.4 1738.56   113.6 1740.15   123.4 1747.77   129.9 1751.62
   136.4 1754.13   159.1 1764.63   168.8 1770.21   178.6 1774.99   185.1 1779.33
   194.8 1786.64   207.8 1793.99   214.3 1798.01   220.8 1803.09   227.3 1809.06
#Mann= 3 , 0 , 0
       0     .12       0    94.2    .045       0   110.4     .12       0
#XS Ineff= 2 , 0
            87.2 1741.08
Permanent Ineff=
       F       F
Bank Sta=94.2,110.4
XS Rating Curve= 0 ,0
Exp/Cntr=0.3,0.1

Type RM Length L Ch R = 1 ,4592.4  ,128.5,126,122.6
XS GIS Cut Line= 3
     2007945.028      252524.185     2007914.336       252675.37
     2007915.324      252769.188
#Sta/Elev= 30
       0 1766.07     6.4 1764.03    16.1 1760.15    25.7 1755.42    32.1 1752.81
    41.8 1749.51    48.2 1748.06    51.4  1746.7    61.1 1740.07    73.9 1729.46
    83.6 1723.16    86.8 1721.76      90  1721.1    99.6 1720.19   109.3 1717.28
   115.7 1716.57   121.4 1717.18   125.3  1719.4     135 1729.47   147.8 1740.34
     151 1742.55   160.7  1747.1   167.2 1751.33   170.4 1754.09   180.2 1763.74
   199.6 1778.98   215.7 1789.62   228.7 1799.18   238.4 1809.18   248.1 1816.71
#Mann= 3 ,-1 , 0
       0     .12       0   109.3    .045       0   121.4     .12       0
Bank Sta=109.3,121.4
XS Rating Curve= 0 ,0
Exp/Cntr=0.3,0.1

Type RM Length L Ch R = 1 ,4466.4  ,154.1,167.8,179.1
XS GIS Cut Line= 2
      2007810.17      252496.984     2007793.481      252737.304
#Sta/Elev= 30
       0 1754.36     9.8 1753.34    16.3 1753.32    29.3 1752.15    39.1 1751.68
    45.6 1749.58    52.1 1746.39    65.1  1738.5    74.9 1733.06    87.9    1724
    94.4 1718.72   100.9 1714.33   104.2 1712.37   107.4 1711.44   110.7 1711.39
   120.4 1711.44   130.2 1712.96   143.2 1713.66   149.8 1715.52     153 1717.17
   172.5 1729.56     179 1734.04   192.1 1744.55   198.6 1750.53   201.8    1753
   208.3 1757.22   218.1 1764.79   227.9  1769.5   237.6 1775.74   240.9  1778.5
#Mann= 3 ,-1 , 0
       0     .12       0   107.4    .045       0   120.4     .12       0
#XS Ineff= 2 , 0
                          131.06         1717.33
Permanent Ineff=
       F       F
Bank Sta=107.4,120.4
XS Rating Curve= 0 ,0
Exp/Cntr=0.3,0.1

Type RM Length L Ch R = 1 ,4298.7  ,168.4,156.2,143.5
XS GIS Cut Line= 3
     2007725.963      252473.651     2007642.201       252594.64
     2007643.169        252710.8
#Sta/Elev= 30
       0 1739.88    16.4 1737.07    26.2  1732.3      36 1726.25    42.5 1721.08
    45.8 1719.02      49 1717.87    58.9 1717.05    62.1  1715.7    68.7 1711.13
    78.5    1702      85 1697.98    91.6 1696.12   104.6 1694.67   111.2 1694.29
  118.811694.652     121 1695.22   127.5 1699.45   130.8 1700.86   143.9 1701.53
   147.2 1703.28   156.8 1711.61   163.3 1716.45   179.4 1724.77   192.3 1732.76
     202 1736.84   221.4 1743.94   250.4 1757.02   256.9 1759.25   263.3 1762.16
#Mann= 3 ,-1 , 0
       0     .12       0   104.6    .045       0  118.81     .12       0
Bank Sta=104.6,118.81
XS Rating Curve= 0 ,0
Exp/Cntr=0.3,0.1

Type RM Length L Ch R = 1 ,4142.4  ,153.2,139.8,123.8
XS GIS Cut Line= 4
     2007541.288      252440.625     2007513.295      252512.609
     2007508.086      252603.755     2007544.699      252702.407
#Sta/Elev= 30
       0 1710.41     9.6 1709.17    16.1 1706.84    32.2 1702.72    38.6 1701.72
    41.8  1700.7    48.3 1697.67    57.9 1691.19    64.4 1688.89    77.2 1682.98
    80.5 1681.99      87 1682.01    93.5 1681.45  105.071678.226   109.8 1677.84
   116.4  1678.2   122.9 1678.41   129.4 1677.78   139.2 1679.54     149 1682.61
   152.2 1682.99     162 1682.88   165.3 1683.26   168.5 1684.45   171.7  1686.9
   178.1 1692.63   181.3 1694.66   225.9 1720.82   251.4 1734.37   273.8 1748.68
#Mann= 3 ,-1 , 0
       0     .12       0  105.07    .045       0   116.4     .12       0
Bank Sta=105.07,116.4
XS Rating Curve= 0 ,0
Exp/Cntr=0.3,0.1

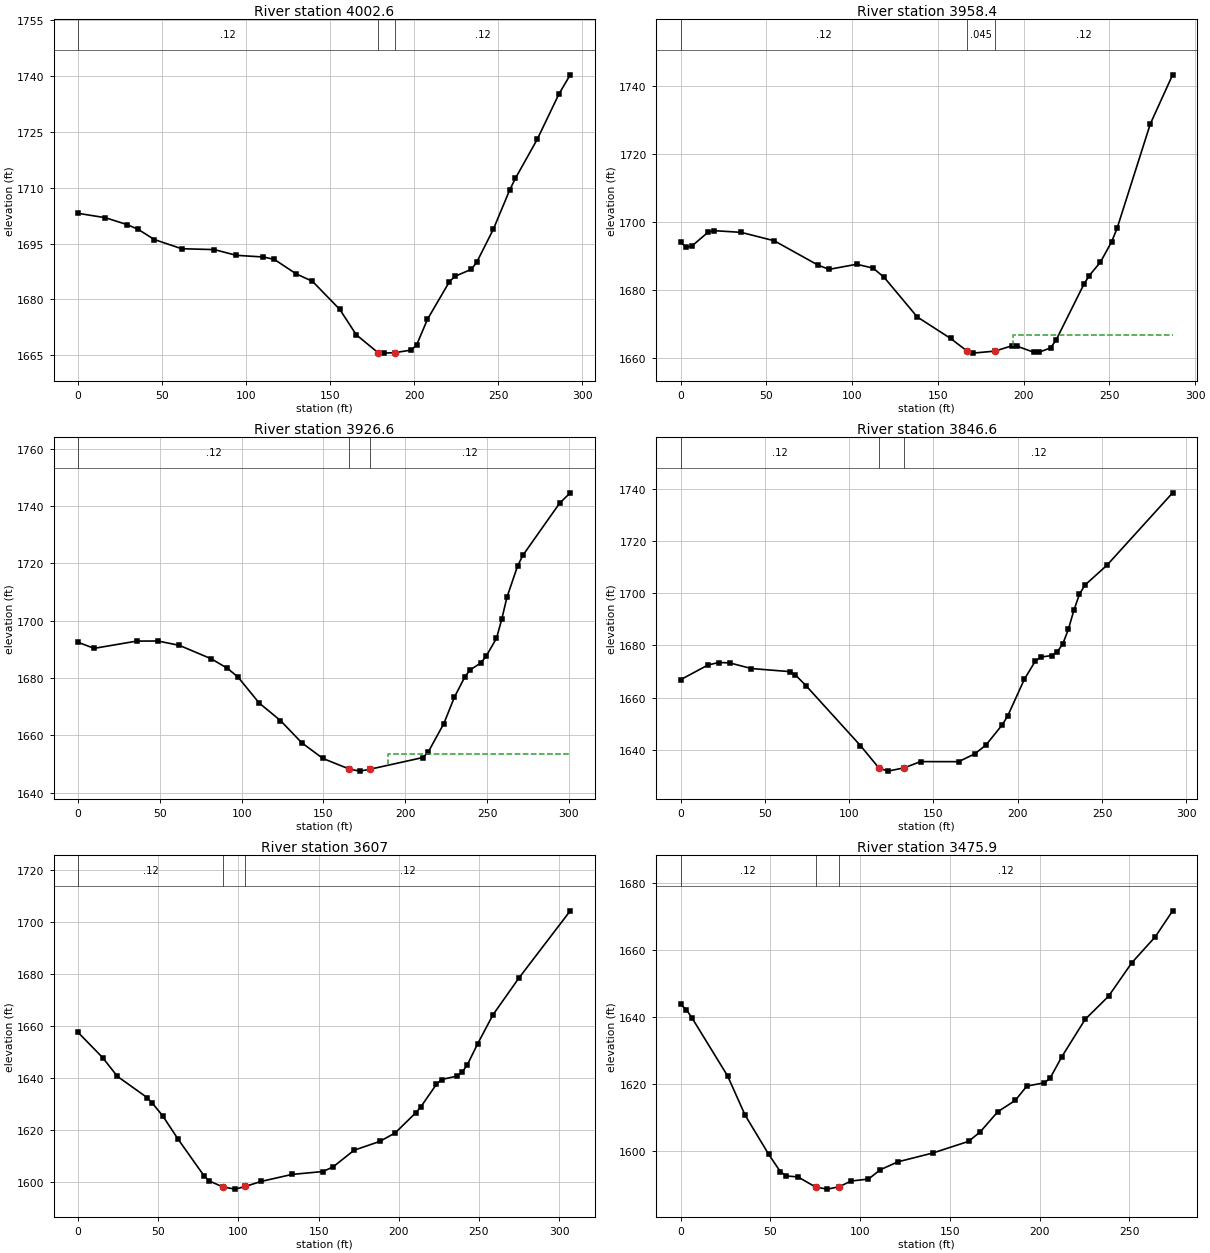
Type RM Length L Ch R = 1 ,4002.6  ,31.9,44.3,56.5
XS GIS Cut Line= 3
      2007469.49      252466.886     2007382.722      252580.193
     2007457.719      252710.389
#Sta/Elev= 30
       0 1703.12    16.2 1701.94    29.2 1700.08    35.7 1698.82    45.4 1696.07
    61.6 1693.61    81.1 1693.37    94.1 1691.84   110.3 1691.38   116.8 1690.74
   129.7 1686.88   139.5 1684.85   155.8 1677.29   165.6 1670.48   178.6 1665.66
   181.9 1665.55   188.4 1665.67   198.2 1666.36   201.5 1667.72     208 1674.65
   221.1 1684.79   224.4 1686.19   234.2  1688.1   237.4 1690.06   247.2 1698.83
     257 1709.45   260.3 1712.48   273.4 1723.06   286.4 1735.31     293 1740.34
#Mann= 3 , 0 , 0
       0     .12       0   178.6    .045       0   188.4     .12       0
Bank Sta=178.6,188.4
XS Rating Curve= 0 ,0
Exp/Cntr=0.3,0.1

Type RM Length L Ch R = 1 ,3958.4  ,31.2,31.8,32.2
XS GIS Cut Line= 3
     2007439.937      252468.279      2007360.51      252581.126
     2007359.642      252729.998
#Sta/Elev= 30
       0 1694.06     3.2 1692.59     6.4  1692.8      16 1696.93    19.3 1697.42
    35.3 1696.91    54.6 1694.45    80.2 1687.29    86.6 1686.05   102.7 1687.55
   112.3 1686.41   118.7 1683.72     138 1672.09   157.4  1665.8   167.1 1662.06
   170.4 1661.47   183.3 1662.06     193 1663.59   196.2 1663.51     206 1661.72
   209.2 1661.78   215.7    1663   218.9 1665.25   235.1 1681.62   238.3 1684.23
   244.8 1688.16   251.3 1694.12   254.5 1698.07   273.9 1728.76   286.9 1743.14
#Mann= 3 , 0 , 0
       0     .12       0   167.1    .045       0   183.3     .12       0
#XS Ineff= 2 , 0
                          193.81         1666.76
Permanent Ineff=
       F       F
Bank Sta=167.1,183.3
XS Rating Curve= 0 ,0
Exp/Cntr=0.3,0.1

Type RM Length L Ch R = 1 ,3926.6  ,78,80,79.7
XS GIS Cut Line= 3
     2007413.896      252465.675     2007330.128      252573.748
     2007325.354       252737.81
#Sta/Elev= 30
       0 1692.41     9.8 1690.31    35.8 1692.84    48.8 1692.87    61.9 1691.35
    81.4 1686.66    91.2 1683.38    97.7 1680.32   110.7 1671.24   123.7 1665.13
   136.7  1657.4   149.6 1651.92   165.7 1648.24   172.1 1647.49   178.6 1648.17
   210.8 1652.23     214 1654.09   223.6 1664.08   230.1 1673.32   236.5 1680.42
   239.7 1682.81   246.2 1685.21   249.4 1687.51   255.8 1693.82     259 1700.43
   262.2 1708.15   268.7 1719.03   271.9 1722.73   294.4 1740.93   300.9 1744.55
#Mann= 3 , 0 , 0
       0     .12       0   165.7    .045       0   178.6     .12       0
#XS Ineff= 2 , 0
                          189.63         1653.58
Permanent Ineff=
       F       F
Bank Sta=165.7,178.6
XS Rating Curve= 0 ,0
Exp/Cntr=0.3,0.1

Type RM Length L Ch R = 1 ,3846.6  ,236.9,239.5,239.3
XS GIS Cut Line= 3
      2007272.14      252460.319     2007258.086      252637.609
     2007289.898       252747.08
#Sta/Elev= 30
       0 1666.86    16.2 1672.49    22.6 1673.47    29.1 1673.33      42 1671.16
    64.7 1669.98    67.9 1668.84    74.4 1664.59   106.7 1641.58   117.61633.028
   122.9  1631.8   132.61633.053   142.3 1635.45   164.9 1635.43   174.6 1638.47
   181.1 1641.81   190.9 1649.66   194.1 1653.11   203.9 1667.07   210.4 1674.04
   213.7 1675.57   220.2 1676.15   223.4 1677.56   226.7 1680.66     230 1686.24
   233.2 1693.43   236.5 1699.59   239.7 1703.12   252.8 1710.76   291.8 1738.57
#Mann= 3 ,-1 , 0
       0     .12       0   117.6    .045       0   132.6     .12       0
Bank Sta=117.6,132.6
XS Rating Curve= 0 ,0
Exp/Cntr=0.3,0.1

Type RM Length L Ch R = 1 ,3607    ,144.2,131.1,117.9
XS GIS Cut Line= 4
     2007062.467      252510.768      2007073.19      252549.067
     2007049.753      252679.276     2007127.218      252789.793
#Sta/Elev= 30
       0 1657.54    15.3 1647.88    24.5 1640.69      43 1632.57    46.2 1630.46
    52.7  1625.6    62.4 1616.55    78.5 1602.56    81.7  1600.6    90.2 1598.28
    97.9 1597.43   104.3 1598.46     114 1600.36   133.4 1603.07   152.7 1604.18
   159.2 1606.02   172.1 1612.34   188.1 1615.72   197.8 1619.01   210.6  1626.7
   213.8 1629.01   223.5 1637.64   226.7 1639.48   236.3 1640.78   239.6 1642.32
   242.8 1645.15   249.2 1653.16   258.8 1664.32   274.9 1678.37     307 1704.21
#Mann= 3 ,-1 , 0
       0     .12       0    90.2    .045       0   104.3     .12       0
Bank Sta=90.2,104.3
XS Rating Curve= 0 ,0
Exp/Cntr=0.3,0.1

Type RM Length L Ch R = 1 ,3475.9  ,176.1,176.4,175.8
XS GIS Cut Line= 3
     2006912.103        252580.5     2006976.836       252737.87
     2007037.091      252822.602
#Sta/Elev= 30
       0 1643.68     3.3 1642.03     6.5 1639.52    26.2 1622.32      36 1610.56
    49.1  1598.9    55.6 1593.73    58.9 1592.44    65.4 1592.16    75.31589.115
    81.8 1588.51    88.4 1589.22    94.9 1590.92   104.7 1591.52   111.3  1594.3
   121.1 1596.66   140.7 1599.32   160.4 1602.76   166.9 1605.57   176.7 1611.61
   186.4 1614.97   192.9 1619.27   202.7 1620.25   205.9 1621.68   212.4 1628.05
   225.4  1639.2   238.4 1646.08   251.4 1656.11   264.4 1663.81   274.1 1671.58
#Mann= 3 ,-1 , 0
       0     .12       0    75.3    .045       0    88.4     .12       0
Bank Sta=75.3,88.4
XS Rating Curve= 0 ,0
Exp/Cntr=0.3,0.1

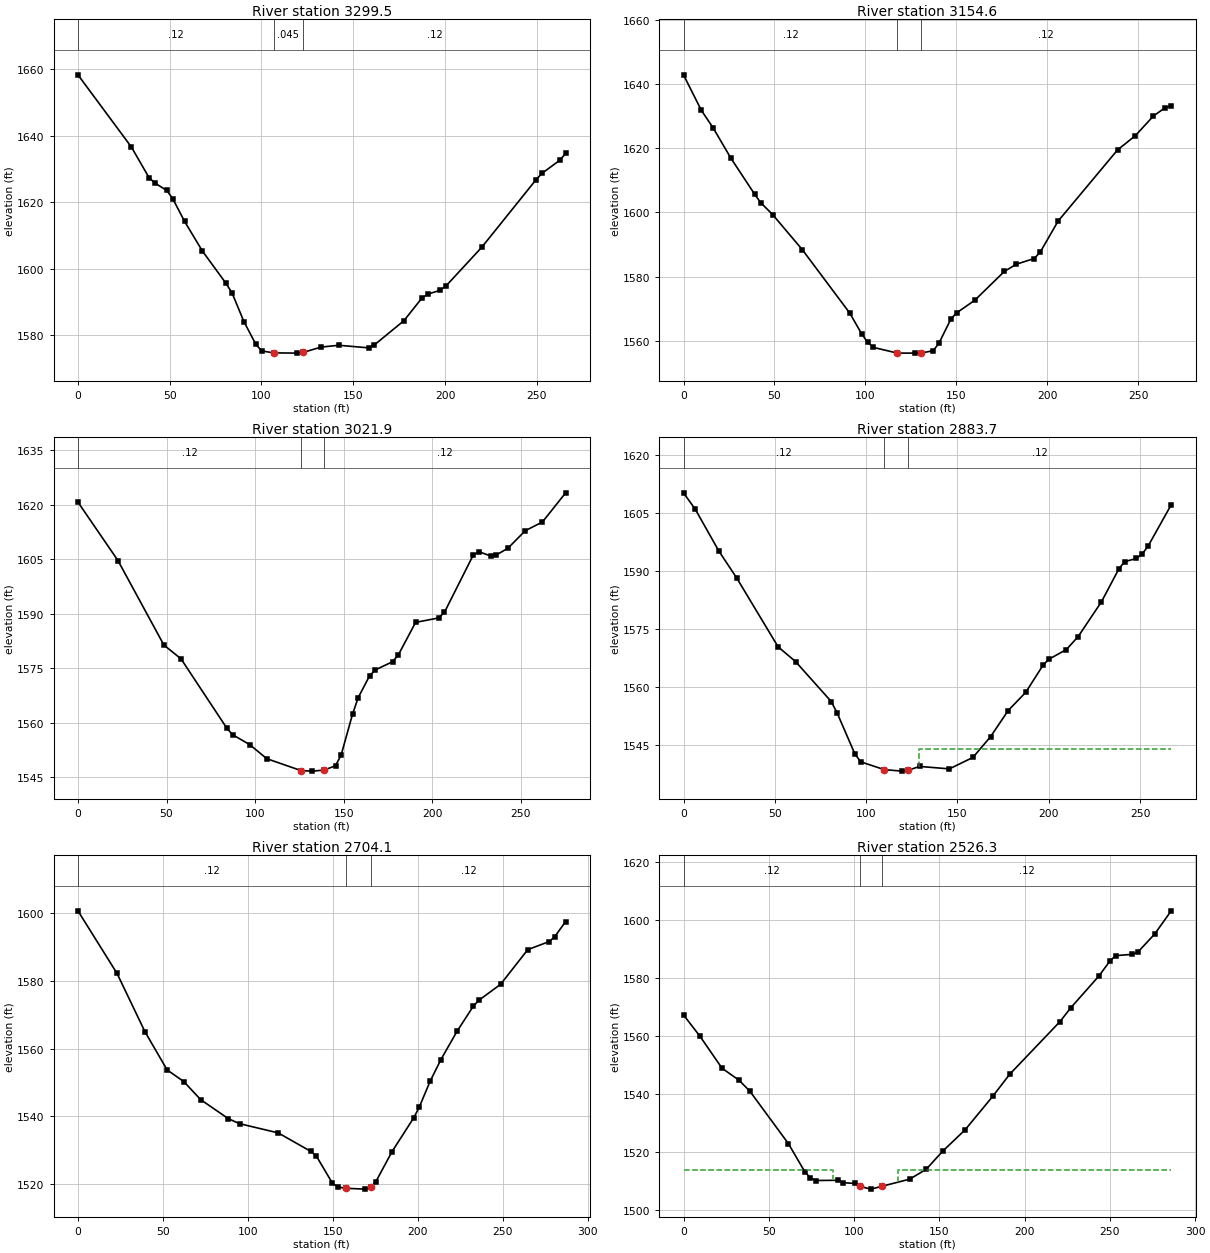
Type RM Length L Ch R = 1 ,3299.5  ,139.5,144.9,146.6
XS GIS Cut Line= 3
     2006754.617       252648.26     2006828.399       252813.39
     2006882.264      252878.965
#Sta/Elev= 30
       0  1658.3    29.1 1636.62    38.8 1627.35      42 1625.76    48.4 1623.54
    51.7 1621.04    58.1 1614.25    67.8 1605.35    80.7  1595.6      84  1592.7
    90.4 1584.16    96.9 1577.33   100.1 1575.32   106.6 1574.74   119.5 1574.66
   122.7 1574.87   132.4 1576.47   142.1 1577.02   158.3 1576.25   161.5 1577.13
   177.6 1584.41   187.4 1591.21   190.7 1592.41   197.2 1593.52   200.4 1594.78
     220 1606.48   249.4 1626.66   252.7 1628.65   262.5 1632.63   265.7 1634.66
#Mann= 3 ,-1 , 0
       0     .12       0   106.6    .045       0   122.7     .12       0
Bank Sta=106.6,122.7
XS Rating Curve= 0 ,0
Exp/Cntr=0.3,0.1

Type RM Length L Ch R = 1 ,3154.6  ,137,132.7,129.2
XS GIS Cut Line= 3
     2006659.557       252677.04     2006661.732      252791.255
     2006711.357      252936.893
#Sta/Elev= 30
       0  1642.9     9.8 1631.84    16.3 1626.36    26.1 1616.87    39.2 1605.61
    42.4 1603.08      49 1599.34    65.3 1588.41    91.4 1568.63    97.9 1562.19
   101.2 1559.54   104.4 1557.94   117.5 1556.18   127.3 1556.16   130.6  1556.2
   137.2  1556.9   140.4 1559.22     147 1566.81   150.2 1568.74   160.1 1572.63
   176.4 1581.64     183 1583.88   192.8 1585.65   196.1 1587.65   205.9  1597.3
   238.6  1619.5   248.4 1623.95   258.3 1630.06   264.8 1632.67   268.1 1633.28
#Mann= 3 ,-1 , 0
       0     .12       0   117.5    .045       0   130.6     .12       0
Bank Sta=117.5,130.6
XS Rating Curve= 0 ,0
Exp/Cntr=0.3,0.1

Type RM Length L Ch R = 1 ,3021.9  ,134.2,138.1,141.5
XS GIS Cut Line= 4
      2006521.82      252717.716     2006525.013      252808.182
     2006562.774      252890.213     2006619.438      252965.765
#Sta/Elev= 30
       0  1620.7    22.6 1604.61    48.5 1581.38    58.2 1577.56    84.1 1558.45
    87.3  1556.7      97 1553.95   106.6 1550.09     1261546.806   132.4 1546.67
   138.9 1546.95   145.4 1548.15   148.6 1551.14     155 1562.34   158.2  1566.9
   164.7 1572.95   167.9 1574.53   177.6 1576.78   180.8  1578.6   190.6  1587.6
   203.6 1588.82   206.9 1590.39   223.2 1606.17   226.4 1607.04   232.9 1605.88
   236.2 1606.17   242.7    1608   252.5 1612.82   262.2 1615.23   275.3 1623.25
#Mann= 3 ,-1 , 0
       0     .12       0     126    .045       0   138.9     .12       0
Bank Sta=126,138.9
XS Rating Curve= 0 ,0
Exp/Cntr=0.3,0.1

Type RM Length L Ch R = 1 ,2883.7  ,167.7,179.7,189.9
XS GIS Cut Line= 3
     2006377.852      252758.699       2006425.1      252926.845
     2006468.006      253008.777
#Sta/Elev= 30
       0 1610.28     6.5 1605.99    19.4  1595.2    29.1  1588.3    51.8 1570.48
    61.4 1566.65    80.9 1556.34    84.1 1553.42    93.8 1542.85      97 1540.76
     110 1538.73   119.7 1538.35   122.9 1538.58   129.4 1539.56   145.6 1538.93
   158.5 1541.89   168.2 1547.27   177.8 1554.01   187.4  1558.7     197  1565.8
   200.2  1567.3   209.7 1569.78   216.1 1573.11   228.9 1582.12   238.4 1590.61
   241.6 1592.49     248 1593.31   251.2 1594.46   254.4 1596.49   267.1  1607.2
#Mann= 3 ,-1 , 0
       0     .12       0     110    .045       0   122.9     .12       0
#XS Ineff= 2 , 0
                          128.79         1543.99
Permanent Ineff=
       F       F
Bank Sta=110,122.9
XS Rating Curve= 0 ,0
Exp/Cntr=0.3,0.1

Type RM Length L Ch R = 1 ,2704.1  ,183.9,177.8,170.6
XS GIS Cut Line= 4
     2006276.274      252777.762     2006267.201      252888.911
     2006245.065      252991.776     2006240.338      253061.902
#Sta/Elev= 30
       0 1600.54      23 1582.13    39.4    1565    52.5 1553.71    62.3 1550.28
    72.2 1544.97    88.6 1539.33    95.1 1537.89   117.9 1535.16     137 1529.74
   140.2 1528.44   149.8 1520.33     153 1519.25   157.6 1518.87   168.9 1518.62
   172.6 1519.25   175.3 1520.81   184.8 1529.63   197.6 1539.62   200.8 1542.69
   207.2 1550.32   213.6 1556.77   223.1 1565.09   232.7 1572.49   235.9  1574.2
   248.7  1578.9   264.7 1589.11   277.4 1591.51   280.6 1592.94     287 1597.39
#Mann= 3 ,-1 , 0
       0     .12       0   157.6    .045       0   172.6     .12       0
Bank Sta=157.6,172.6
XS Rating Curve= 0 ,0
Exp/Cntr=0.3,0.1

Type RM Length L Ch R = 1 ,2526.3  ,104.2,80.9,56.4
XS GIS Cut Line= 4
     2006095.369      252794.397     2006084.909      252874.588
     2006090.118      252942.297     2006129.861      253073.672
#Sta/Elev= 30
       0 1567.33     9.7 1559.93    22.6 1548.95    32.4  1544.9    38.8 1541.14
    61.5 1522.99    71.2 1513.23    74.4 1511.19    77.6 1510.28    90.6 1510.36
    93.8 1509.54   100.3 1509.26   103.5 1508.22     110 1507.31   116.4  1508.3
   132.6 1510.74   142.3 1514.13     152 1520.39   165.1 1527.72   181.5  1539.4
   191.3 1546.89   220.7 1564.98   227.2 1569.85   243.6 1580.73   250.1 1585.93
   253.4 1587.75   263.2 1588.19   266.4 1588.94   276.2 1595.12     286 1603.18
#Mann= 3 ,-1 , 0
       0     .12       0   103.5    .045       0   116.4     .12       0
#XS Ineff= 2 , 0
           87.93 1513.99  126.01         1513.99
Permanent Ineff=
       F       F
Bank Sta=103.5,116.4
XS Rating Curve= 0 ,0
Exp/Cntr=0.3,0.1

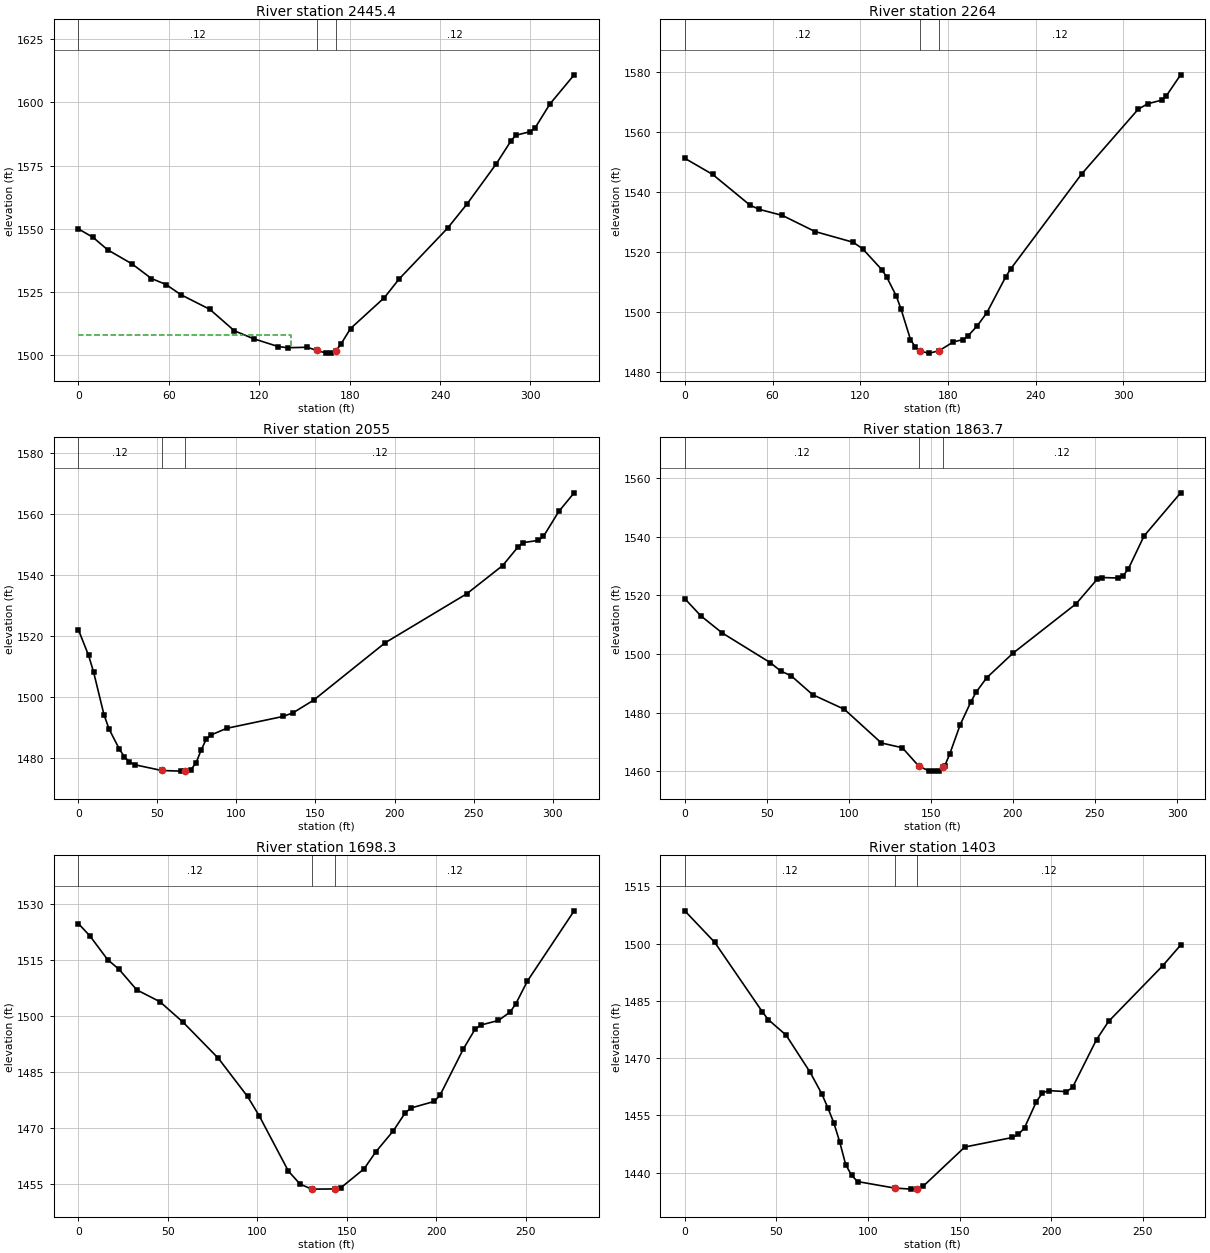
Type RM Length L Ch R = 1 ,2445.4  ,133.1,181.4,226.3
XS GIS Cut Line= 4
      2006023.24      252798.726     2006010.046      252930.671
     2006058.657      252954.976     2006103.796      253089.698
#Sta/Elev= 30
       0 1549.92     9.7 1546.58    19.4 1541.64    35.6 1536.04    48.5 1530.24
    58.2 1527.87    67.9 1523.88    87.3 1518.01   103.5 1509.54   116.4 1506.36
   132.6 1503.29     139 1502.81   151.8 1503.01   158.2 1501.76   164.6 1500.68
   167.8 1500.68     171 1501.63   174.2  1504.2   180.6 1510.42   203.1 1522.68
   212.8 1530.02   245.1 1550.26     258 1559.84   277.4 1575.75   287.1 1584.79
   290.3 1587.02     300 1588.44   303.2 1590.04   312.9 1599.38     329 1610.95
#Mann= 3 , 0 , 0
       0     .12       0   158.2    .045       0     171     .12       0
#XS Ineff= 2 , 0
          141.23 1507.91
Permanent Ineff=
       F       F
Bank Sta=158.2,171
XS Rating Curve= 0 ,0
Exp/Cntr=0.3,0.1

Type RM Length L Ch R = 1 ,2264    ,229.3,209,188.3
XS GIS Cut Line= 4
     2005997.693      252792.463     2005988.555      252881.099
     2005881.784      252967.036     2005882.767      253080.025
#Sta/Elev= 30
       0 1551.35    19.1 1545.96    44.6 1535.74    50.9 1534.34    66.8  1532.3
    89.1 1526.94   115.2 1523.37   121.7 1521.17   134.8 1514.22   138.1 1511.81
   144.6 1505.53   147.8 1501.29   154.4 1490.94   157.6 1488.51   160.9 1487.02
   167.4 1486.42     174 1487.22   183.7 1490.15   190.3 1490.93   193.5    1492
   200.1 1495.54   206.6 1499.85   219.6 1511.89   222.9 1514.45   271.4 1546.07
   310.1 1567.66   316.6 1569.52   326.2 1570.72   329.5 1572.21   339.2 1579.17
#Mann= 3 ,-1 , 0
       0     .12       0   160.9    .045       0     174     .12       0
Bank Sta=160.9,174
XS Rating Curve= 0 ,0
Exp/Cntr=0.3,0.1

Type RM Length L Ch R = 1 ,2055    ,201.7,191.3,180.4
XS GIS Cut Line= 3
     2005753.229      252767.821     2005755.482      252968.338
     2005784.733      253077.543
#Sta/Elev= 30
       0 1522.14     6.5 1513.67     9.7 1508.14    16.2 1494.32    19.4 1489.62
    25.9 1483.04    29.1 1480.51    32.3 1478.82    35.6  1477.9    52.7 1476.01
    64.7  1475.8    67.7 1475.84    71.2 1476.31    74.4 1478.42    77.6 1482.61
    80.9 1486.26    84.1 1487.67    93.8 1489.81   129.4 1493.69   135.8  1494.9
   148.8 1499.03   194.1 1517.84   245.8 1533.91   268.4 1543.12     278 1549.14
   281.3 1550.62     291 1551.34   294.2 1552.66   303.9 1560.84   313.6 1566.92
#Mann= 3 ,-1 , 0
       0     .12       0    52.7    .045       0    67.7     .12       0
Bank Sta=52.7,67.7
XS Rating Curve= 0 ,0
Exp/Cntr=0.3,0.1

Type RM Length L Ch R = 1 ,1863.7  ,156.5,165.4,173
XS GIS Cut Line= 4
     2005577.395      252787.673      2005573.19      252878.495
     2005638.295      253007.401     2005639.224      253074.294
#Sta/Elev= 30
       0 1518.89     9.7 1513.06    22.7 1507.22      52 1497.08    58.4 1494.22
    64.9 1492.52    77.9 1486.12    97.3  1481.1   119.8 1469.62   132.6 1467.99
   142.61461.724   148.7 1460.13   151.9 1460.01   155.1 1460.12   157.61461.307
   158.3 1461.64   161.5 1465.89   167.9 1475.92   174.4  1483.7   177.6 1487.01
     184 1491.88     200 1500.26   238.5 1517.14   251.3  1525.5   254.4 1526.11
     264 1525.93   267.2 1526.68   270.4 1529.14   279.9 1540.28   302.2 1555.02
#Mann= 3 ,-1 , 0
       0     .12       0   142.6    .045       0   157.6     .12       0
Bank Sta=142.6,157.6
XS Rating Curve= 0 ,0
Exp/Cntr=0.3,0.1

Type RM Length L Ch R = 1 ,1698.3  ,280.8,295.4,307.6
XS GIS Cut Line= 2
     2005424.751      252793.403     2005454.249      253068.725
#Sta/Elev= 30
       0 1524.77     6.5 1521.43    16.3 1515.13    22.8 1512.46    32.6    1507
    45.6 1503.81    58.6 1498.27    78.2 1488.65    94.5 1478.41     101 1473.25
   117.3 1458.42   123.8 1454.95   130.3 1453.58   143.3 1453.63   146.6 1453.94
   159.6 1459.03   166.1 1463.56   175.9  1469.2   182.4 1473.93   185.7 1475.32
   198.7 1477.08     202 1478.76     215 1491.14   221.5  1496.4   224.8 1497.57
   234.6 1498.79   241.1 1501.03   244.3 1503.24   250.8 1509.36   276.9 1528.18
#Mann= 3 ,-1 , 0
       0     .12       0   130.3    .045       0   143.3     .12       0
Bank Sta=130.3,143.3
XS Rating Curve= 0 ,0
Exp/Cntr=0.3,0.1

Type RM Length L Ch R = 1 ,1403    ,204.7,198.9,192.1
XS GIS Cut Line= 3
     2005246.041      252773.093     2005161.732      252934.484
     2005155.425       253022.78
#Sta/Elev= 30
       0  1508.6    16.3 1500.36    42.3 1482.16    45.5 1480.12    55.3 1476.02
    68.3 1466.38    74.8 1460.62      78 1457.05    81.3 1453.09    84.5 1448.13
    87.8 1442.11      91 1439.31    94.3 1437.66   114.5 1435.96   123.6 1435.68
   126.8  1435.8   130.1 1436.44   152.8 1446.71   178.8 1449.21   182.1 1450.02
   185.4 1451.75   191.9 1458.63   195.2 1460.88   198.5  1461.5   208.3 1461.22
   211.6 1462.32   224.7 1474.86   231.3 1479.64   260.8  1494.2   270.6 1499.62
#Mann= 3 ,-1 , 0
       0     .12       0   114.5    .045       0   126.8     .12       0
Bank Sta=114.5,126.8
XS Rating Curve= 0 ,0
Exp/Cntr=0.3,0.1

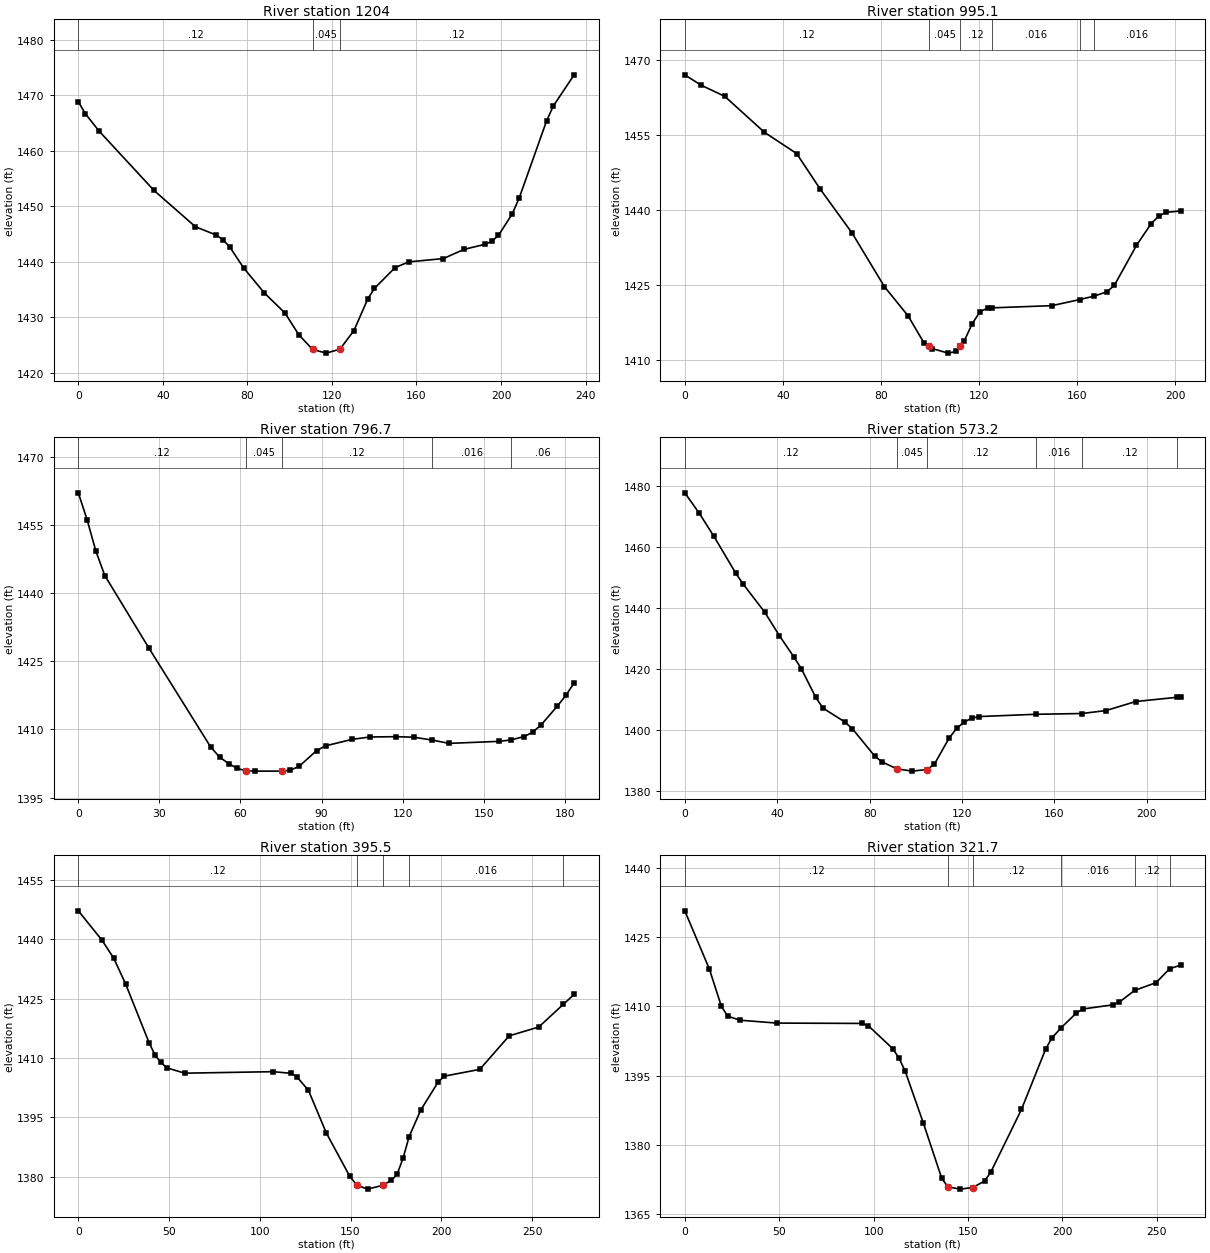
Type RM Length L Ch R = 1 ,1204    ,205.6,208.9,211.5
XS GIS Cut Line= 2
     2005018.777       252732.29     2004971.587      252962.122
#Sta/Elev= 30
       0 1468.86     3.3  1466.7     9.8 1463.57    35.8 1452.86    55.4 1446.32
    65.2 1444.83    68.4 1443.99    71.7 1442.65    78.2  1438.9      88 1434.39
    97.8 1430.76   104.3 1426.86   110.8 1424.21   117.3 1423.54   123.8 1424.26
   130.4  1427.6   136.9 1433.28   140.1 1435.21   149.9 1438.96   156.4 1439.99
   172.7 1440.58   182.5 1442.24   192.3 1443.14   195.5 1443.66   198.8 1444.76
   205.3 1448.63   208.6  1451.5   221.6 1465.45   224.8 1468.12   234.6  1473.7
#Mann= 3 ,-1 , 0
       0     .12       0   110.8    .045       0   123.8     .12       0
Bank Sta=110.8,123.8
XS Rating Curve= 0 ,0
Exp/Cntr=0.3,0.1

Type RM Length L Ch R = 1 ,995.1   ,196.3,198.4,198.3
XS GIS Cut Line= 3
     2004831.907      252695.231     2004776.315      252855.057
     2004777.484      252888.064
#Sta/Elev= 30
       0 1467.04     6.5 1465.01    16.3 1462.74    32.5 1455.55    45.6 1451.32
    55.3 1444.16    68.3 1435.38    81.4 1424.73    91.1 1418.87    97.6 1413.44
   99.521412.814   100.9 1412.36   107.4 1411.45   110.6 1411.78  112.271412.823
   113.9 1413.84   117.2 1417.31   120.4 1419.74   123.7 1420.47  125.221420.494
   149.7 1420.93   161.11422.155  166.861422.829   172.2 1423.71   175.2 1425.01
   184.2 1432.97   190.2 1437.32   193.2 1438.78   196.2 1439.56   202.2 1439.85
#Mann= 6 ,-1 , 0
       0     .12       0   99.52    .045       0  112.27     .12       0
  125.22    .016       0   161.1     .12       0  166.86    .016       0
Bank Sta=99.52,112.27
XS Rating Curve= 0 ,0
Exp/Cntr=0.3,0.1

Type RM Length L Ch R = 1 ,796.7   ,234.5,223.5,211.1
XS GIS Cut Line= 3
     2004648.012       252653.92     2004597.502      252781.541
     2004600.483      252827.699
#Sta/Elev= 30
       0 1462.11     3.3 1456.07     6.5 1449.25     9.8 1443.89    26.1 1427.93
      49 1406.11    52.3 1403.89    55.6 1402.49    58.8 1401.39    62.1  1400.9
    65.4 1400.81    75.2 1400.82    78.4 1400.99    81.7 1401.86    88.2 1405.34
    91.5 1406.38   101.3  1407.8   107.8 1408.33   117.6  1408.4   124.2 1408.28
  131.05 1407.64   137.2 1406.92   155.8 1407.37   160.21407.688     165 1408.43
   168.1 1409.36   171.2 1410.96   177.3 1415.14   180.4 1417.48   183.5 1420.23
#Mann= 5 ,-1 , 0
       0     .12       0    62.1    .045       0    75.2     .12       0
  131.05    .016       0   160.2     .06       0
Bank Sta=62.1,75.2
XS Rating Curve= 0 ,0
Exp/Cntr=0.3,0.1

Type RM Length L Ch R = 1 ,573.2   ,158.6,177.8,194.1
XS GIS Cut Line= 3
     2004429.679      252606.924     2004398.711      252668.859
     2004419.355      252812.696
#Sta/Elev= 30
       0 1477.68     6.3 1470.95    12.6 1463.43      22 1451.43    25.2 1447.85
    34.6 1438.58    40.9 1430.95    47.2 1423.93    50.4 1420.14    56.7 1410.66
    59.8 1407.17    69.2 1402.66    72.5 1400.44    82.2 1391.46    85.4 1389.54
    91.8 1387.28    98.3 1386.53   104.8 1387.04     108 1388.77   114.4 1397.34
   117.7 1400.56   120.9 1402.59   124.1 1403.84   127.4  1404.4  151.851405.148
  171.911405.398   182.3 1406.37   195.2 1409.33  213.021410.711   214.6 1410.85
#Mann= 6 ,-1 , 0
       0     .12       0    91.8    .045       0   104.8     .12       0
  151.85    .016       0  171.91     .12       0  213.02     .06       0
Bank Sta=91.8,104.8
XS Rating Curve= 0 ,0
Exp/Cntr=0.3,0.1

Type RM Length L Ch R = 1 ,395.5   ,74.6,73.7,74.2
XS GIS Cut Line= 2
     2004322.021      252586.659     2004163.555      252809.224
#Sta/Elev= 30
       0 1447.15      13 1439.75    19.5  1435.2      26 1428.74      39 1413.83
    42.3 1410.68    45.5 1408.85    48.8  1407.5    58.6 1406.15   107.3 1406.53
   117.1 1406.12   120.3 1405.29   126.8 1401.81   136.6 1391.09   149.6 1380.07
  153.551377.831   159.4 1376.87   167.6 1377.82   172.4 1379.05   175.6 1380.59
   178.9 1384.64  182.241390.076   188.6 1396.78   198.4 1404.02   201.7  1405.4
   221.2 1407.11   237.4 1415.58   253.7 1417.81  267.281423.561   273.2 1426.05
#Mann= 5 ,-1 , 0
       0     .12       0  153.55    .045       0   167.6     .12       0
  182.24    .016       0  267.28     .12       0
Bank Sta=153.55,167.6
XS Rating Curve= 0 ,0
Exp/Cntr=0.3,0.1

Type RM Length L Ch R = 1 ,321.7   ,155.3,155.9,155.9
XS GIS Cut Line= 2
     2004249.199      252566.798     2004095.326      252779.536
#Sta/Elev= 30
       0 1430.72      13 1418.11    19.4 1409.98    22.7 1407.89    29.2    1407
    48.6 1406.38      94  1406.3    97.2  1405.8   110.2 1400.81   113.4 1398.81
   116.7 1395.96   126.4 1384.63   136.1 1372.69   139.4 1370.85   145.9 1370.37
   152.4 1370.71   158.8 1372.12   162.1 1374.09   178.3 1387.65   191.2 1400.82
   194.5 1403.19  199.441405.418   207.4 1408.56   210.7 1409.42   226.9 1410.35
   230.1 1410.91  238.25 1413.46   249.6 1415.15  256.821418.174   262.6 1418.94
#Mann= 6 ,-1 , 0
       0     .12       0   139.4    .045       0   152.4     .12       0
  199.44    .016       0  238.25     .12       0  256.82     .06       0
Bank Sta=139.4,152.4
XS Rating Curve= 0 ,0
Exp/Cntr=0.3,0.1

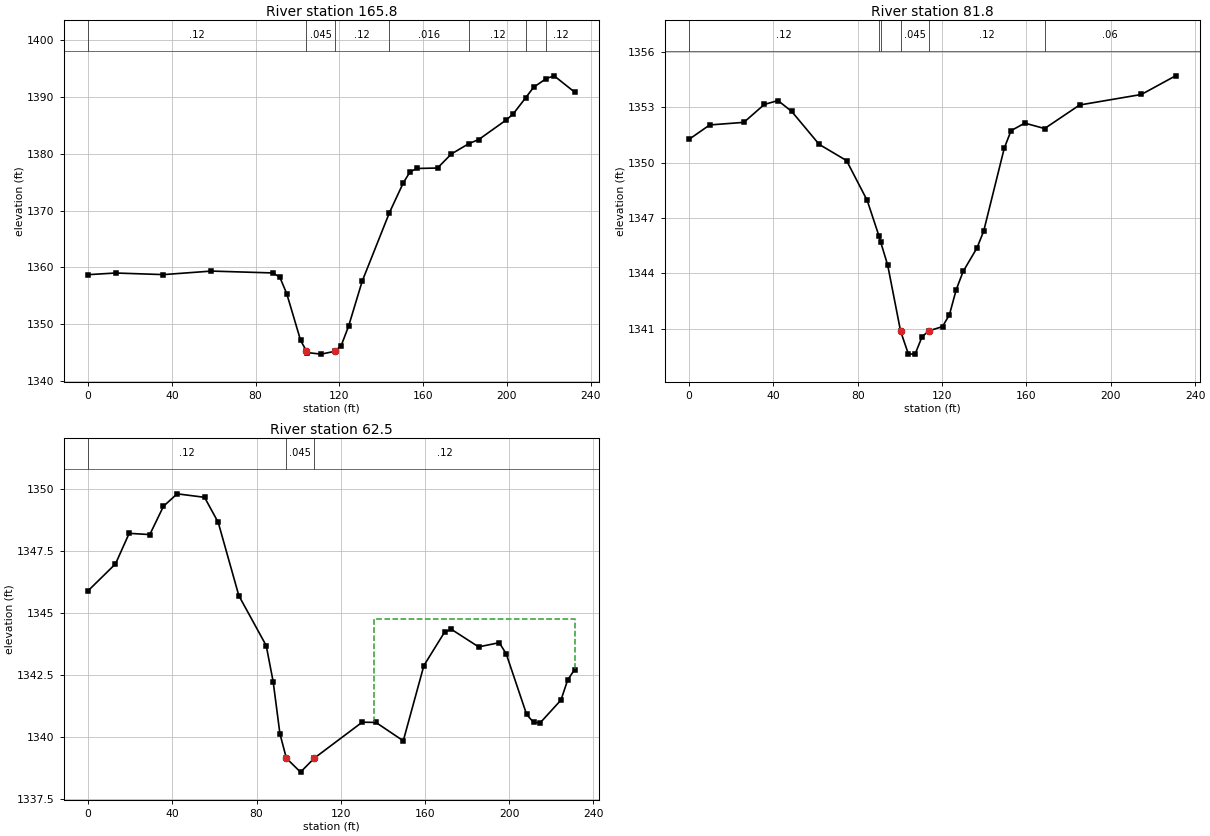
Type RM Length L Ch R = 1 ,165.8   ,83.7,84,84.3
XS GIS Cut Line= 2
     2004100.422      252510.957     2003961.346       252697.15
#Sta/Elev= 30
       0 1358.72    13.1 1359.01      36 1358.73    58.9 1359.35    88.4 1359.02
    91.6 1358.25    94.9 1355.35   101.5 1347.15  104.261345.304   104.7 1345.01
   111.3 1344.74   117.8 1345.23   120.9 1346.25   124.4 1349.63   130.9 1357.55
  143.961369.655   150.6 1374.91   153.8 1376.82   157.1  1377.4   166.9 1377.48
   173.5 1379.95  181.961381.792   186.6 1382.49   199.7 1385.93   202.9 1386.93
  209.031389.848   212.8 1391.69  218.831393.212   222.6  1393.7   232.4 1390.83
#Mann= 7 ,-1 , 0
       0     .12       0  104.26    .045       0   117.8     .12       0
  143.96    .016       0  181.96     .12       0  209.03    .016       0
  218.83     .12       0
Bank Sta=104.26,117.8
XS Rating Curve= 0 ,0
Exp/Cntr=0.3,0.1

Type RM Length L Ch R = 1 ,81.8    ,19.2,19.3,19.1
XS GIS Cut Line= 2
     2004030.767      252467.214     2003890.069      252650.064
#Sta/Elev= 30
       0 1351.26     9.8 1352.04      26 1352.18    35.7 1353.15    42.2 1353.36
    48.7 1352.77    61.7 1350.99    74.7 1350.11    84.5 1347.95   90.061346.029
    90.9 1345.69    94.2 1344.45  100.321340.873     104 1339.64   107.2 1339.63
   110.5 1340.57   113.7 1340.89   120.2 1341.12   123.5 1341.77   126.7 1343.12
     130 1344.11   136.5 1345.37   139.7 1346.28   149.5 1350.79   152.7 1351.73
   159.2 1352.14  168.611351.845   185.2 1353.12   214.5 1353.69   230.7  1354.7
#Mann= 6 ,-1 , 0
       0     .12       0   90.06     .08       0    90.9     .12       0
  100.32    .045       0   113.7     .12       0  168.61     .06       0
Bank Sta=100.32,113.7
XS Rating Curve= 0 ,0
Exp/Cntr=0.3,0.1

Type RM Length L Ch R = 1 ,62.5    ,63.9,62.5,61.2
XS GIS Cut Line= 2
     2004015.188      252456.446     2003874.363      252639.688
#Sta/Elev= 30
       0  1345.9      13 1346.98    19.5 1348.21    29.3 1348.16    35.8  1349.3
    42.3  1349.8    55.3 1349.66    61.8 1348.65    71.6  1345.7    84.6 1343.69
    87.9 1342.24    91.1 1340.15   94.151339.162   100.9  1338.6   107.4 1339.16
   130.2 1340.61   136.7  1340.6   149.7 1339.86   159.5 1342.89   169.3 1344.23
   172.5 1344.35   185.5 1343.64   195.3 1343.81   198.6 1343.36   208.3 1340.92
   211.6  1340.6   214.8 1340.59   224.6  1341.5   227.8 1342.31   231.1 1342.73
#Mann= 3 ,-1 , 0
       0     .12       0   94.15    .045       0   107.4     .12       0
#XS Ineff= 2 , 0
                          135.96         1344.77
Permanent Ineff=
       F       F
Bank Sta=94.15,107.4
XS Rating Curve= 0 ,0
Exp/Cntr=0.3,0.1

Chan Stop Cuts=-1
Use User Specified Reach Order=0
Composite Channel Slope=5